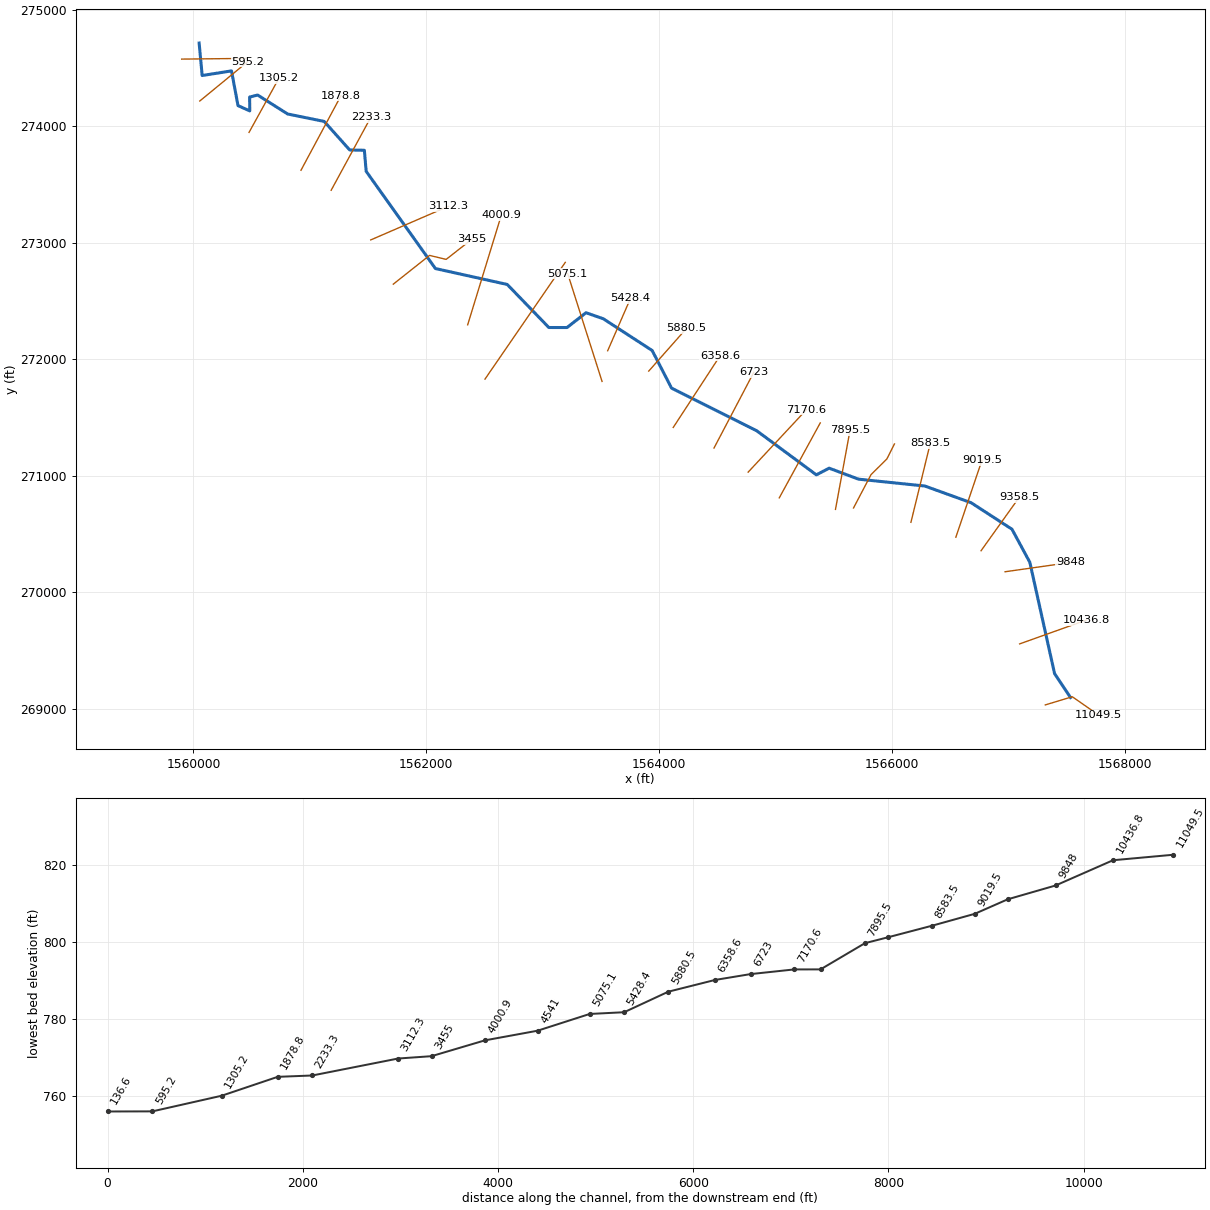
--- LYNNCMPRN.prj (project) ---

Proj Title=LYNNCMPRN
Current Plan=p01
Default Exp/Contr=0,0
English Units
Geom File=g01
Flow File=f01
Plan File=p01
BEGIN DESCRIPTION:
END DESCRIPTION:
DSS Export Rating Curves= 0
DSS Export Rating Curve Sorted= 0
DSS Export Volume Flow Curves= 0
DXF OffsetX= 0
DXF OffsetY= 0
DXF ScaleX= 0
DXF ScaleY= 0

--- LYNNCMPRN.p01 (plan) ---

Plan Title=Floodplain
Program Version=4.00
Geom File=g01
Flow File=f01
K Sum by GR=0
Std Step Tol=0.01
Critical Tol=0.01
Num of Std Step Trials=20
Max Error Tol=0.3
Flow Tol Ratio=0.001
Split Flow NTrial=30
Split Flow Tol=0.02
Split Flow Ratio=0.02
Log Output Level=0
Friction Slope Method=1
Unsteady Friction Slope Method=2
Unsteady Bridges Friction Slope Method=1
Global Log Level=0
CheckData=False
Run HTab=0
Run UNet=0
Run PostProcess=0
UNET Theta=0
UNET Theta Warmup=0
UNET ZTol=0
UNET ZSATol=0
UNET MxIter=0
UNET MaxInSteps=0
UNET DtIC=0
UNET DtMin=0
UNET MaxCRTS=0
UNET WFStab=0
UNET SFStab=0
UNET WFX=0
UNET SFX=0
UNET DSS MLevel=0
UNET DZMax Abort=0
UNET Convert EG Bridges=0
UNET Use Existing IB Tables=0
UNET Froude Limit=0
UNET Froude Power=0
Write IC File=0
Echo Input=False
Echo Output=False
Write Detailed=0

--- LYNNCMPRN.f01 (steady flow) ---

Flow Title=NFF Regression Equation
Program Version=4.00
Number of Profiles=1
Profile Names=P100yr
River Rch & RM=LYNNCMPRN,Main      ,11049.5
901.2944
River Rch & RM=LYNNCMPRN,Main      ,9848
963.8409
River Rch & RM=LYNNCMPRN,Main      ,7895.5
1008.573
River Rch & RM=LYNNCMPRN,Main      ,7440.2
1135.615
River Rch & RM=LYNNCMPRN,Main      ,5075.1
1227.230
River Rch & RM=LYNNCMPRN,Main      ,4541
1502.744
River Rch & RM=LYNNCMPRN,Main      ,595.2
1597.736
River Rch & RM=LYNNCMPRN,Main      ,136.6
1603.391
Boundary for River Rch & Prof#=LYNNCMPRN,Main      ,1
Up Type=0
Dn Type=3
Dn Slope=0.004612

--- LYNNCMPRN.g01 (geometry) ---

Geom Title=USGS 10m DEM
Program Version=4.10

River Reach=LYNNCMPRN       ,Main
Reach XY= 30
     1567534.562      269095.669     1567397.618      269300.662
      1567184.95      270256.367     1567031.566      270540.116
     1566680.734      270767.444     1566283.275      270910.878
     1565713.375      270969.722     1565461.038      271064.157
     1565351.422       271006.66     1564839.308      271384.898
     1564107.385      271751.252     1563941.067      272073.875
     1563521.622      272346.097     1563373.011      272398.211
      1563209.47      272271.128     1563053.559      272271.287
     1562695.928      272640.919     1562079.261      272777.378
     1561484.384      273611.739     1561468.844      273792.482
     1561342.803      273795.086     1561124.053      274039.877
     1560809.529      274104.049     1560552.158      274266.579
     1560483.358      274249.119     1560484.469      274130.503
     1560383.428      274175.815     1560327.702      274473.834
     1560075.615      274434.148     1560049.586      274712.429

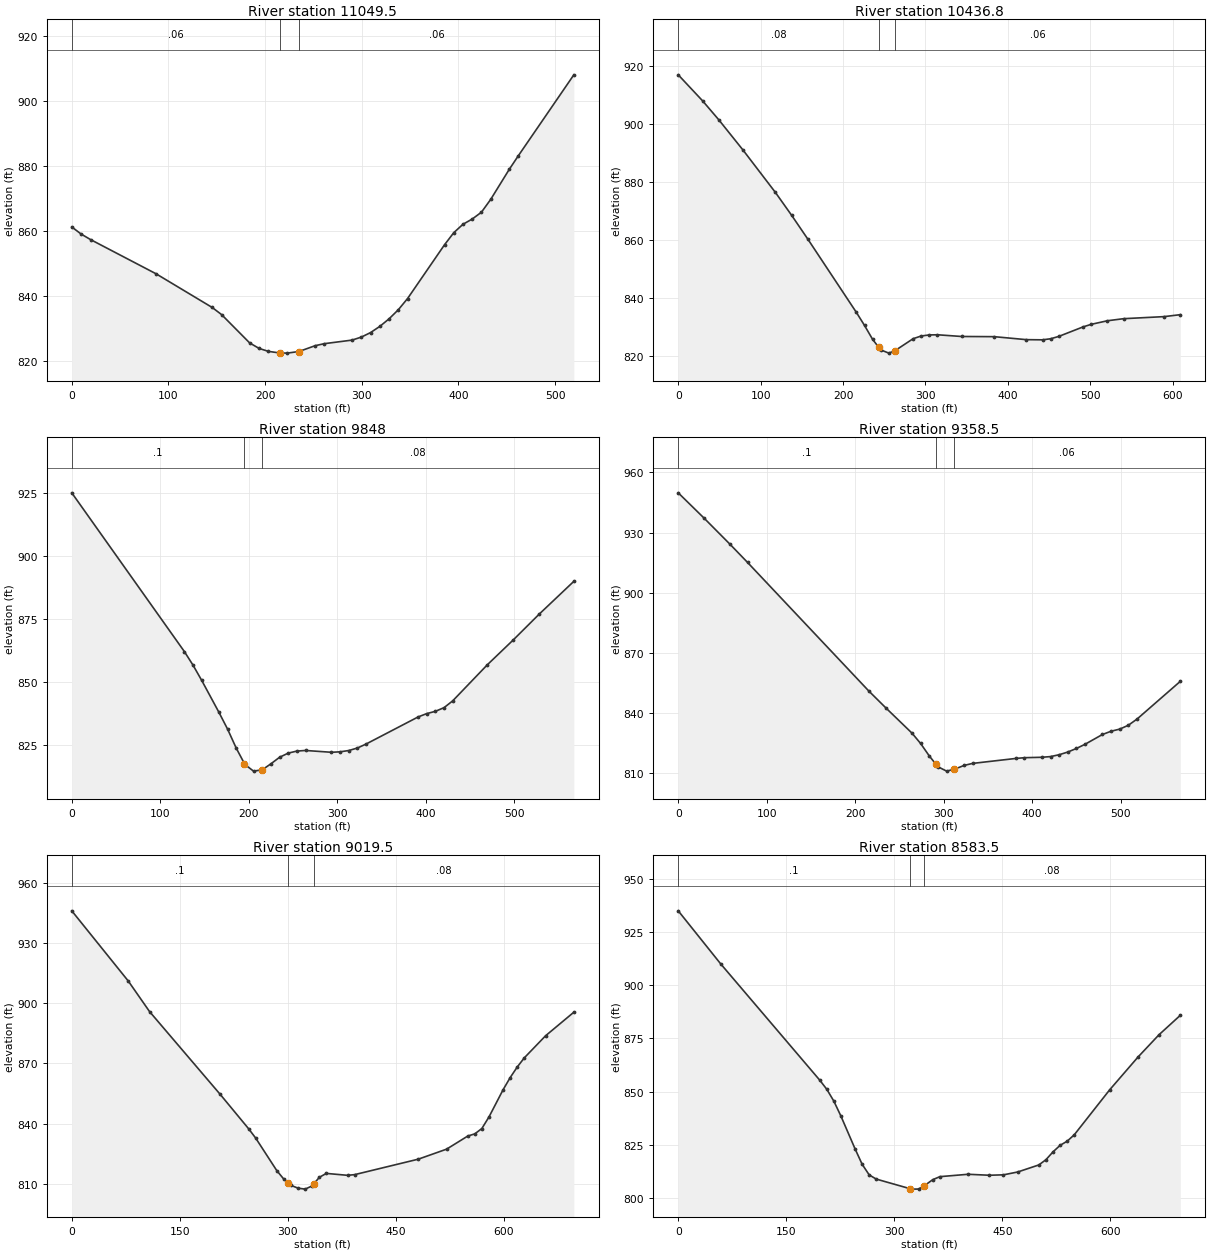
Type RM Length L Ch R = 1 ,11049.5 ,608.1,612.8,633.5
XS GIS Cut Line= 3
     1567317.822      269032.091     1567549.593      269102.403
     1567777.298      268944.241
#Sta/Elev= 30
       0  861.38     9.7  859.19    19.4   857.5    87.2  846.97   145.3   836.6
     155  834.41   184.1  825.68   193.8  824.01   203.4   823.1     215 822.617
   222.8  822.56     235823.0574   251.8  824.85   261.3  825.47     290  826.57
   299.6   827.5   309.1  828.88   318.7  830.79   328.2   833.1   337.8   835.9
   347.4  839.36   385.6  855.89   395.2  859.62   404.7   862.2   414.3  863.82
   423.8  865.91   433.4  869.86   452.5  879.06   462.1  883.34   519.4  908.18
#Mann= 3 , 0 , 0
       0     .06       0     215    .045       0     235     .06       0
Bank Sta=215,235
XS Rating Curve= 0 ,0
Exp/Cntr=0.3,0.1

Type RM Length L Ch R = 1 ,10436.8 ,593,588.8,584.2
XS GIS Cut Line= 2
     1567097.515      269555.832     1567671.444      269760.839
#Sta/Elev= 30
       0  916.82    29.5   907.9    49.2  901.37    78.6  890.97     118  876.37
   137.6  868.54   157.3  860.34   216.2  835.16   226.1  830.67   235.9  825.89
   243.2823.2009   245.7  822.28   255.6  821.15   263.2822.0119   285.1  826.11
   294.9  827.04   304.7   827.4   314.6  827.46     344  826.87   383.4  826.81
   422.7  825.78   442.3  825.72   452.2   826.1     462  826.91   491.5  830.18
   501.3  831.05     521  832.28   540.6  832.99   589.8   833.7   609.4  834.37
#Mann= 3 , 0 , 0
       0     .08       0   243.2    .045       0   263.2     .06       0
Bank Sta=243.2,263.2
XS Rating Curve= 0 ,0
Exp/Cntr=0.3,0.1

Type RM Length L Ch R = 1 ,9848    ,470.7,489.5,507
XS GIS Cut Line= 2
     1566972.408      270175.069     1567534.257      270254.568
#Sta/Elev= 30
       0  925.23   127.2  862.16     137  856.75   146.8   850.7   166.3  837.99
   176.1   831.3   185.9  823.72   195.2817.5611   195.7  817.23   205.4  814.61
   215.2  815.13     225   817.5   234.8  820.11   244.6  821.77   254.4  822.58
   264.2  822.82   293.5   822.1   303.3  822.29   313.1   822.8   322.9  823.81
   332.6  825.38   391.3  836.13   401.1  837.47   410.9  838.38   420.7  839.84
   430.5  842.54   469.6  856.87     499  866.78   528.3  877.03   567.4  890.05
#Mann= 3 , 0 , 0
       0      .1       0   195.2    .045       0   215.2     .08       0
Bank Sta=195.2,215.2
XS Rating Curve= 0 ,0
Exp/Cntr=0.3,0.1

Type RM Length L Ch R = 1 ,9358.5  ,332.3,339,345.6
XS GIS Cut Line= 2
     1566766.155      270355.522     1567096.154      270817.144
#Sta/Elev= 30
       0  949.86    29.4  937.15    58.7  924.12    78.3  915.16   215.2  851.08
   234.8  842.51   264.2  829.98   273.9  824.84   283.7  818.62   291.1814.5424
   293.5  813.22   303.3  811.04   311.1811.9133   313.1  812.14   322.9  813.86
   332.6  814.89   381.6  817.37   391.3  817.74   410.9  817.95   420.7  818.29
   430.5  819.22   440.3  820.57     450  822.35   459.8  824.45   479.4  829.32
   489.2  830.94     499  832.01   508.7  833.93   518.5  837.01   567.4  855.83
#Mann= 3 , 0 , 0
       0      .1       0   291.1    .045       0   311.1     .06       0
Bank Sta=291.1,311.1
XS Rating Curve= 0 ,0
Exp/Cntr=0.3,0.1

Type RM Length L Ch R = 1 ,9019.5  ,434.1,436,438
XS GIS Cut Line= 2
     1566549.531      270471.494     1566773.644      271131.568
#Sta/Elev= 30
       0  946.18    78.5  911.12     108  895.89   206.2  854.52   245.4  837.47
   255.3  832.78   284.7  816.49   294.5  812.22   300.7810.2911   304.4  809.14
   314.2  807.76     324  807.27   333.8  808.89   335.7809.7121   343.6  813.13
   353.4  815.12   382.9  814.16   392.7   814.5   481.1  822.22   520.4  827.22
   549.8  833.76   559.6  834.86   569.4  837.53   579.3  843.32   598.9   856.9
   608.7  862.94   618.5  868.22   628.4  872.83   657.8   883.8   697.1  895.58
#Mann= 3 , 0 , 0
       0      .1       0   300.7    .045       0   335.7     .08       0
Bank Sta=300.7,335.7
XS Rating Curve= 0 ,0
Exp/Cntr=0.3,0.1

Type RM Length L Ch R = 1 ,8583.5  ,457.7,452.3,445.4
XS GIS Cut Line= 2
     1566163.781      270599.445     1566329.675      271276.499
#Sta/Elev= 30
       0  934.98    58.9  910.07   196.4  855.44   206.2  851.15     216  845.58
   225.8  838.59   245.4  823.21   255.3  815.91   265.1  810.89   274.9  808.92
   321.3804.4604   323.8   804.2   333.8  804.24   341.3805.7095   353.4  808.65
   363.3  810.06   402.5  811.18     432  810.72   451.6  810.92   471.3  812.25
   500.7  815.57   510.5  818.02   520.4  821.72   530.2  824.78     540  826.72
   549.8  829.71   598.9  850.82   638.2  866.21   667.6  876.78   697.1  885.88
#Mann= 3 , 0 , 0
       0      .1       0   321.3    .045       0   341.3     .08       0
Bank Sta=321.3,341.3
XS Rating Curve= 0 ,0
Exp/Cntr=0.3,0.1

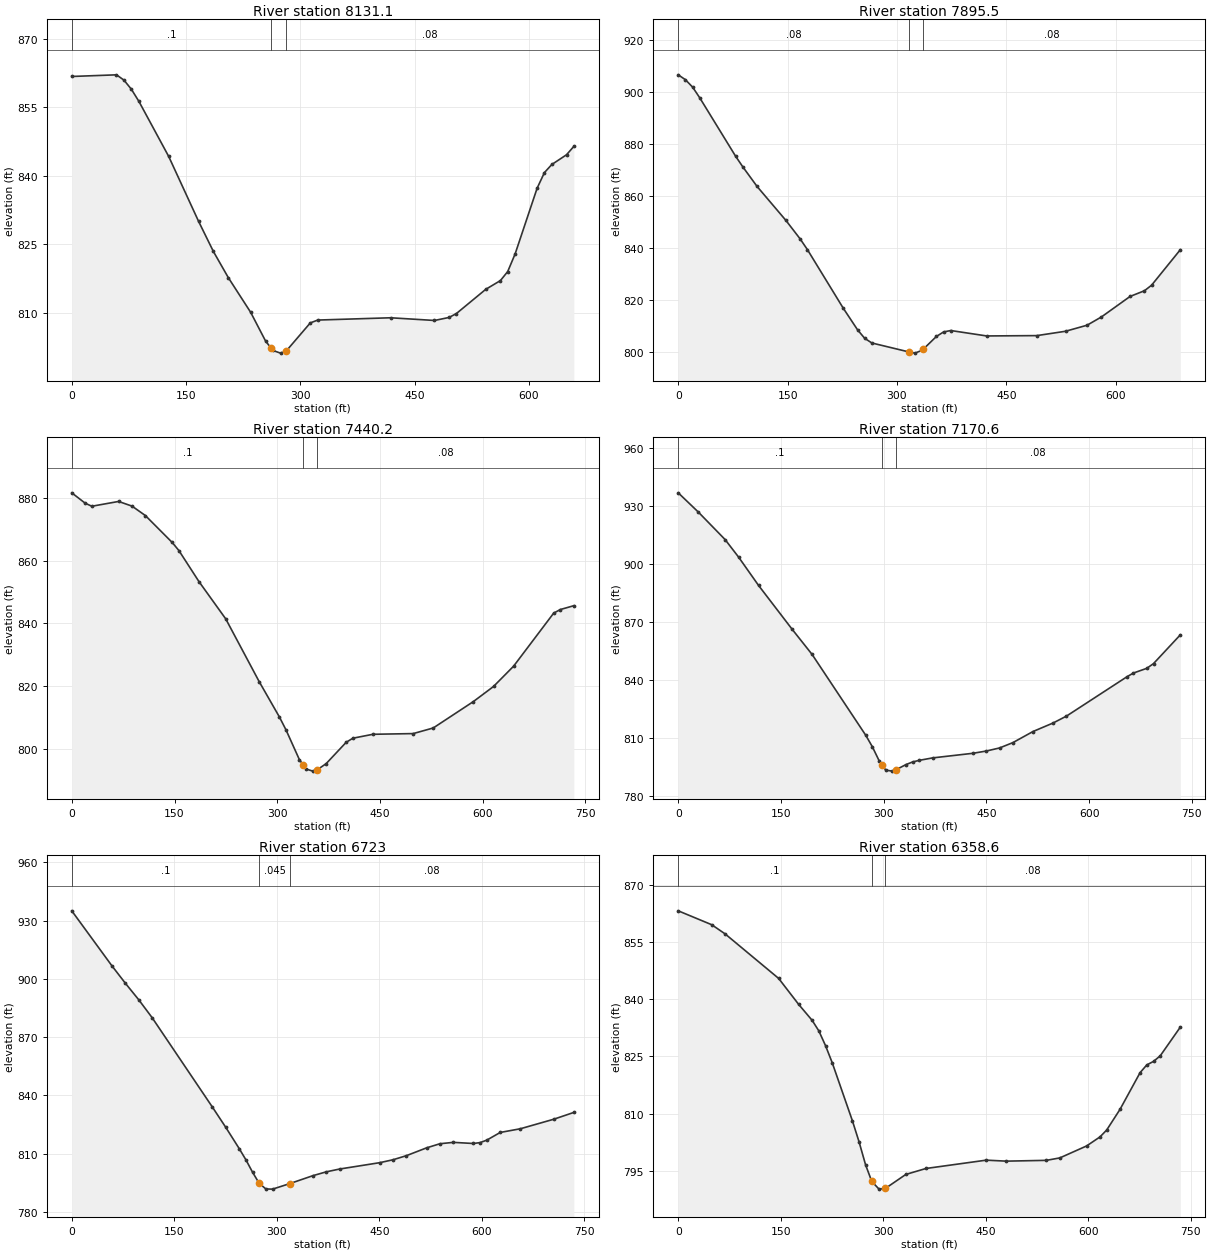
Type RM Length L Ch R = 1 ,8131.1  ,228.1,235.7,243.1
XS GIS Cut Line= 4
     1565670.601      270722.476     1565820.697      271008.379
     1565956.891      271142.957     1566022.038      271272.066
#Sta/Elev= 30
       0  861.77    58.7  862.13    68.5  860.97    78.3  858.96    88.1  856.32
   127.2  844.27   166.4  830.07   185.9  823.45   205.5  817.72   234.8  810.14
   254.4  803.84   261.6 802.311   264.1  801.78     274   801.2   281.6801.6896
   313.1  807.82   322.9  808.44   418.6  808.94   476.1  808.35   495.2  809.01
   504.8  809.86   543.3  815.16   562.6  817.08   572.2  819.06   581.9  822.91
   610.8  837.31   620.4  840.73   630.1   842.5   649.4  844.63     659  846.46
#Mann= 3 , 0 , 0
       0      .1       0   261.6    .045       0   281.6     .08       0
Bank Sta=261.6,281.6
XS Rating Curve= 0 ,0
Exp/Cntr=0.3,0.1

Type RM Length L Ch R = 1 ,7895.5  ,460.9,455.3,448
XS GIS Cut Line= 2
     1565515.661      270710.279     1565640.239      271387.613
#Sta/Elev= 30
       0  906.45     9.8  904.59    19.7  901.74    29.5  897.64    78.7  875.22
    88.6  871.13   108.2  863.61   147.6  850.63   167.2  843.51   177.1  839.43
   226.3  816.94     246  808.61   255.8  805.35   265.6  803.57   316.4800.1341
   324.7  799.68   334.5  800.77   336.4801.2651   354.2  806.09     364  807.81
   373.9  808.35   423.1  806.27   491.9   806.4   531.3  808.07   560.8  810.39
   580.5  813.56   619.8  821.43   639.5  823.61   649.3  825.74   688.7  839.35
#Mann= 3 , 0 , 0
       0     .08       0   316.4    .045       0   336.4     .08       0
Bank Sta=316.4,336.4
XS Rating Curve= 0 ,0
Exp/Cntr=0.3,0.1

Type RM Length L Ch R = 1 ,7440.2  ,274.8,269.6,263.3
XS GIS Cut Line= 2
     1565032.853      270809.247     1565384.679      271452.366
#Sta/Elev= 30
       0  881.64    19.6  878.33    29.3  877.36    68.4  878.89      88   877.4
   107.5  874.39   146.6  865.82   156.4  863.24   185.7  853.34   224.8  841.45
   273.7  821.41     303  810.23   312.8  806.05   332.3  796.58   338.2794.7679
   342.1  793.57   351.9  792.89   358.2793.2868   371.4  795.27   400.7  802.09
   410.5  803.39   439.8  804.64   498.5  804.86   527.8  806.65   586.4  815.07
   615.8  819.88   645.1  826.35   703.7  843.29   713.5  844.43   733.1  845.65
#Mann= 3 , 0 , 0
       0      .1       0   338.2    .045       0   358.2     .08       0
Bank Sta=338.2,358.2
XS Rating Curve= 0 ,0
Exp/Cntr=0.3,0.1

Type RM Length L Ch R = 1 ,7170.6  ,441.1,447.6,453.3
XS GIS Cut Line= 2
     1564765.818      271030.336     1565266.133      271566.123
#Sta/Elev= 30
       0  936.86    29.3  926.92    68.4  912.69      88  903.67   117.3  888.94
   166.2  866.32   195.5  853.23   273.7  811.49   283.4  805.51   293.2  798.35
   297.7796.0679     303  793.38   312.8  792.88   317.7793.5512   332.3  796.23
   342.1  797.61   351.9  798.46   371.4  799.72   430.1   802.1   449.6  803.26
   469.2  804.87   488.7  807.64     518  813.37   547.4  817.79   566.9  821.35
   654.9  841.64   664.6  843.62   684.2  846.07     694  848.52   733.1  863.38
#Mann= 3 , 0 , 0
       0      .1       0   297.7    .045       0   317.7     .08       0
Bank Sta=297.7,317.7
XS Rating Curve= 0 ,0
Exp/Cntr=0.3,0.1

Type RM Length L Ch R = 1 ,6723    ,366.4,364.4,362.1
XS GIS Cut Line= 2
     1564472.413      271237.185     1564814.226      271887.415
#Sta/Elev= 30
       0  935.05    58.8  906.69    78.4  897.75      98  889.22   117.5  880.04
   205.7  833.97   225.3  823.51   244.9   812.6   254.7  806.83   264.5  800.39
   274.1794.7289     284  791.75   293.8  791.67   319.1794.5322   352.6  798.58
   372.2  800.56   391.8  802.02   450.6   805.3   470.1  806.81   489.7  808.92
   519.1  812.93   538.7  815.06   558.3  815.76   587.7  815.18   597.5  815.65
   607.3  816.93   626.9  820.87   656.2  822.76   705.2  827.68   734.6  831.19
#Mann= 3 , 0 , 0
       0      .1       0   274.1    .045       0   319.1     .08       0
Bank Sta=274.1,319.1
XS Rating Curve= 0 ,0
Exp/Cntr=0.3,0.1

Type RM Length L Ch R = 1 ,6358.6  ,481.7,478.1,474.5
XS GIS Cut Line= 2
     1564122.209      271413.864     1564524.239      272028.686
#Sta/Elev= 30
       0  863.25      49   859.6    68.6  857.19   146.9   845.5   176.3  838.65
   195.9  834.49   205.7  831.72   215.5  827.84   225.3  823.35   254.7  808.17
   264.5  802.61   274.2  796.48   283.2792.1637   293.8  790.15   303.2790.3517
     333  794.01   362.4  795.57   450.6  797.76   479.9   797.5   538.7  797.71
   558.3  798.35   597.5  801.49   617.1  803.87   626.9  805.68   646.4  811.11
   675.8  820.76   685.6  822.78   695.4   823.7   705.2  825.16   734.6   832.7
#Mann= 3 , 0 , 0
       0      .1       0   283.2    .045       0   303.2     .08       0
Bank Sta=283.2,303.2
XS Rating Curve= 0 ,0
Exp/Cntr=0.3,0.1

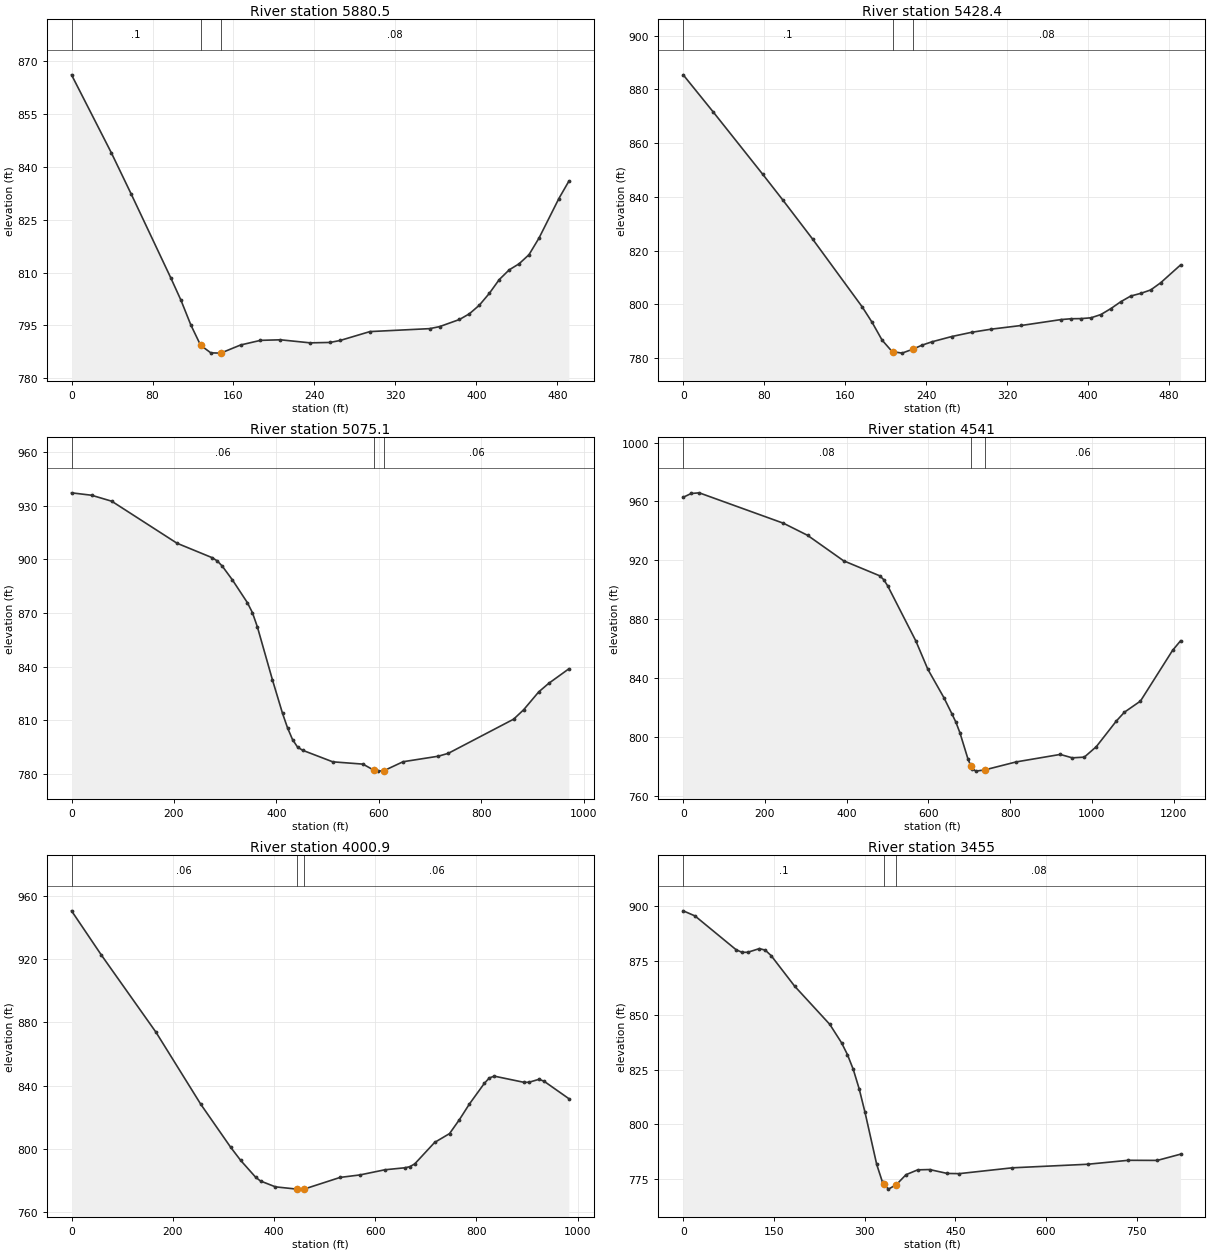
Type RM Length L Ch R = 1 ,5880.5  ,445,452.1,459.2
XS GIS Cut Line= 2
     1563911.605      271897.254     1564237.178      272265.262
#Sta/Elev= 30
       0  866.21    39.3  844.07      59   832.3    98.3  808.36   108.1  802.16
   117.9  795.11   127.5789.3597   137.6  787.19   147.4  787.11   147.5787.1215
   167.1  789.43   186.7  790.74   206.4   790.9   235.8  790.03   255.5  790.15
   265.3   790.7   294.8  793.23   353.8  794.07   363.6  794.64   383.3  796.67
   393.1  798.29   402.9  800.72   412.7  804.06   422.6  808.01   432.4  810.77
   442.2   812.5     452  815.09   461.9  819.82   481.5  831.04   491.4  835.99
#Mann= 3 , 0 , 0
       0      .1       0   127.5    .045       0   147.5     .08       0
Bank Sta=127.5,147.5
XS Rating Curve= 0 ,0
Exp/Cntr=0.3,0.1

Type RM Length L Ch R = 1 ,5428.4  ,337.4,353.3,369.1
XS GIS Cut Line= 2
     1563558.962      272072.115     1563755.296      272522.538
#Sta/Elev= 30
       0  885.46    29.5   871.7    78.6   848.4    98.3  838.89   127.8  824.31
   176.9     799   186.7  793.23   196.5  786.65   206.4  782.39   207.3782.3371
   216.2   781.8   227.3783.3262   235.8  784.74   245.7  786.01   265.3  787.98
     285  789.56   304.6  790.74   334.1   792.1   373.4   794.3   383.3  794.61
   393.1  794.66   402.9  794.96   412.7  796.17   422.6   798.4   432.4  800.96
   442.2  803.07     452  804.05   461.9  805.33   471.7  807.99   491.4  814.64
#Mann= 3 , 0 , 0
       0      .1       0   207.3    .045       0   227.3     .08       0
Bank Sta=207.3,227.3
XS Rating Curve= 0 ,0
Exp/Cntr=0.3,0.1

Type RM Length L Ch R = 1 ,5075.1  ,553.1,534.1,513.1
XS GIS Cut Line= 2
     1563510.571      271808.498     1563215.224      272733.902
#Sta/Elev= 30
       0  937.38    39.2  936.02    78.5  932.68     206  909.12   274.7  901.02
   284.6  899.22   294.4  896.29     314  888.65   343.4  875.83   353.2  870.28
     363  862.22   392.5  832.44   412.1  813.74   421.9  805.62   431.7  799.02
   441.5  794.82   451.4  793.04   510.2  786.57   569.1  785.28   590.1781.9495
   598.5  781.35   610.1  781.59   647.6  786.62   716.3  789.71   735.9  791.33
   863.5  810.48   883.1  815.76   912.5  825.77   932.1  830.57   971.4  838.71
#Mann= 3 , 0 , 0
       0     .06       0   590.1    .045       0   610.1     .06       0
Bank Sta=590.1,610.1
XS Rating Curve= 0 ,0
Exp/Cntr=0.3,0.1

Type RM Length L Ch R = 1 ,4541    ,532.8,540.1,546.3
XS GIS Cut Line= 2
     1562505.071      271828.559     1563194.815      272830.784
#Sta/Elev= 30
       0  962.87    19.6  965.43    39.2  965.88   245.3  945.23   304.2  937.04
   392.5  919.73   480.8  909.56   490.6  906.94   500.4  902.65   569.1  865.35
   598.5  846.09   637.8  826.82   657.4  815.83   667.2  810.15     677  802.95
   696.6  785.22   703.3780.8067   706.4  778.76   716.2  777.01   738.3777.8862
   814.4  783.26   922.3  788.34   951.7  786.03   981.2  786.51  1010.6  793.63
  1059.6  811.04  1079.3     817  1118.5  824.54    1197  858.93  1216.6  865.46
#Mann= 3 , 0 , 0
       0     .08       0   703.3    .045       0   738.3     .06       0
Bank Sta=703.3,738.3
XS Rating Curve= 0 ,0
Exp/Cntr=0.3,0.1

Type RM Length L Ch R = 1 ,4000.9  ,559,545.9,531.6
XS GIS Cut Line= 2
      1562356.25      272294.549     1562644.719      273233.962
#Sta/Elev= 30
       0  950.58      59  922.58   167.1  873.67   255.5  828.14   314.5  800.97
   334.1  792.73   363.6   782.1   373.4  779.65   402.9  775.95     445774.5247
     452  774.51     460774.5827   530.7  781.92     570   783.5   619.1  786.75
   658.4  788.01   668.2  788.68   678.1  790.46   717.4  804.04   746.9  809.64
   766.5  818.51   786.2  828.38   815.6   841.4   825.5  844.86   835.3  845.99
   894.3  842.06   904.1  842.14   923.7  843.99   933.6  842.78   982.7  831.74
#Mann= 3 , 0 , 0
       0     .06       0     445    .045       0     460     .06       0
Bank Sta=445,460
XS Rating Curve= 0 ,0
Exp/Cntr=0.3,0.1

Type RM Length L Ch R = 1 ,3455    ,348.6,342.7,336.8
XS GIS Cut Line= 4
     1561717.178      272643.199     1562028.658      272890.192
     1562171.258       272855.95      1562390.36      273027.421
#Sta/Elev= 30
       0  897.73    19.4  895.41    87.3  879.97      97  878.77   106.6  878.76
     126  880.45   135.7  879.74   145.4  877.24   184.2  863.29   242.4  845.78
   261.8  837.38   271.5     832   281.2   825.2   290.9  816.38   300.6  805.58
     320  781.69   329.6  773.52   332.5772.6017   339.4  770.42   352.5772.4768
   368.4  777.02   387.8  779.24   407.3  779.38   436.6   777.6   456.2   777.5
   544.2  780.17   668.9   781.8     736  783.61     784  783.56   822.4  786.41
#Mann= 3 , 0 , 0
       0      .1       0   332.5    .045       0   352.5     .08       0
Bank Sta=332.5,352.5
XS Rating Curve= 0 ,0
Exp/Cntr=0.3,0.1

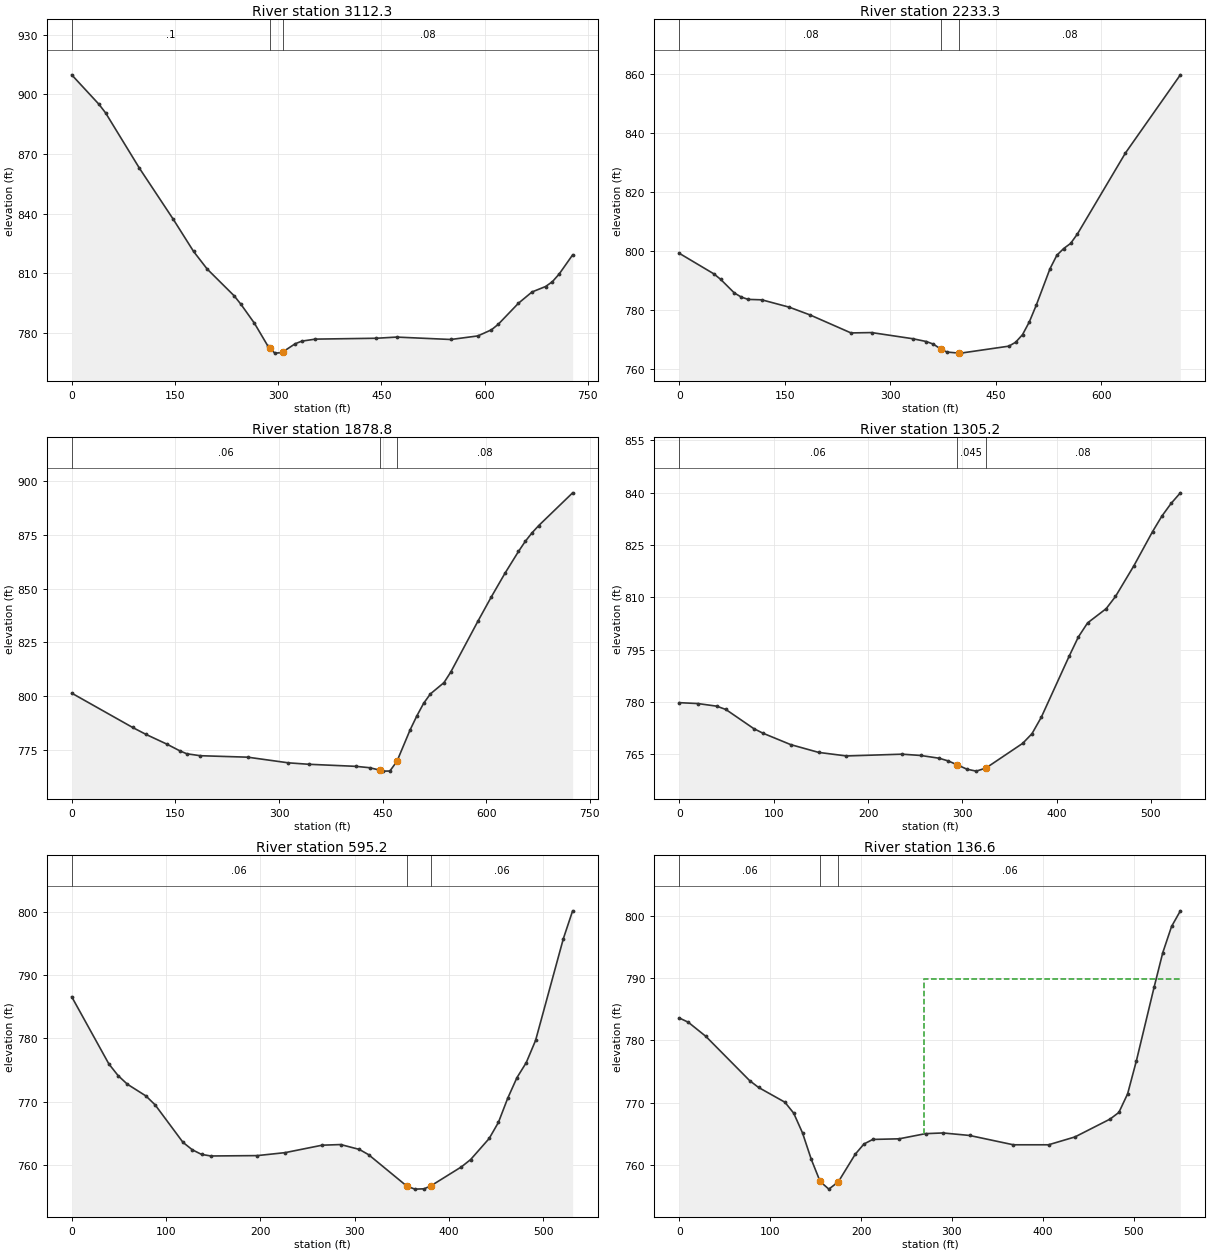
Type RM Length L Ch R = 1 ,3112.3  ,862.9,879,888.9
XS GIS Cut Line= 2
      1561523.66      273022.978     1562191.821       273312.14
#Sta/Elev= 30
       0   909.8    39.4  895.06    49.2  890.68    98.4  862.84   147.6  837.14
   177.1  820.97   196.8  812.14   236.1  798.64     246  794.35   265.6  784.82
   285.3  773.26   287.5772.4924   295.2  769.81     305  770.03   307.5 770.581
   324.7  774.51   334.5  775.85   354.2  776.86   442.7  777.29   472.2  777.88
     551  776.67   590.3  778.47     610  781.54   619.8  784.28   649.3  794.92
     669  800.58   688.7  803.32   698.5  805.72   708.4  809.58     728  819.23
#Mann= 3 , 0 , 0
       0      .1       0   287.5    .045       0   307.5     .08       0
Bank Sta=287.5,307.5
XS Rating Curve= 0 ,0
Exp/Cntr=0.3,0.1

Type RM Length L Ch R = 1 ,2233.3  ,353.8,354.5,357.1
XS GIS Cut Line= 2
     1561183.749      273449.387     1561523.979      274075.029
#Sta/Elev= 30
       0  799.19    48.8  792.28    58.5  790.42      78   785.8    87.8  784.42
    97.6  783.62   117.1  783.47   156.1  780.98   185.4  778.38   243.9  772.26
   273.2  772.38   331.7   770.3   351.2  769.34     361  768.46   372.2766.6949
   380.5  765.78   397.2765.4305     400  765.42   468.3  767.78     478  769.11
   487.8  771.69   497.5  776.03   507.3  781.65   526.8  793.98   536.6  798.57
   546.3  800.84   556.1  802.56   565.8  805.76   634.1  833.19   712.2  859.66
#Mann= 3 , 0 , 0
       0     .08       0   372.2    .045       0   397.2     .08       0
Bank Sta=372.2,397.2
XS Rating Curve= 0 ,0
Exp/Cntr=0.3,0.1

Type RM Length L Ch R = 1 ,1878.8  ,573,573.6,572.1
XS GIS Cut Line= 2
     1560924.468      273620.972     1561267.319      274259.767
#Sta/Elev= 30
       0  801.35    88.2  785.38   107.8  782.11   137.2  777.71   156.8  774.46
   166.6  773.14   186.2  772.24   254.7  771.56   313.5  768.93   342.9  768.26
   411.5  767.29   431.1  766.66   445.7765.5547   450.7  765.07   460.5  765.12
   470.7769.6186   489.9  784.34   499.6   790.8   509.4  796.64   519.2  801.01
   538.8  806.24   548.6  811.14   587.8  834.75   607.4  846.17     627  857.07
   646.6  867.24   656.4  871.93   666.2  875.91     676  879.32     725  894.53
#Mann= 3 , 0 , 0
       0     .06       0   445.7    .045       0   470.7     .08       0
Bank Sta=445.7,470.7
XS Rating Curve= 0 ,0
Exp/Cntr=0.3,0.1

Type RM Length L Ch R = 1 ,1305.2  ,711.4,710,699.1
XS GIS Cut Line= 2
      1560478.28      273945.645     1560734.804      274410.823
#Sta/Elev= 30
       0  779.81    19.7  779.55    39.4  778.81    49.2  777.86    78.7  772.39
    88.5  771.06     118  767.78   147.6  765.55   177.1  764.53   236.1  765.04
   255.8  764.67   275.4  763.88   285.3  763.08   294.1762.0294     305  760.72
   314.8  760.18   325.1761.0779     364  768.15   373.8   770.9   383.7  775.62
   413.2   793.1     423  798.64   432.8  802.68   452.5  806.76   462.4  810.26
     482  819.11   501.7  828.86   511.6  833.31   521.4  836.95   531.2  839.98
#Mann= 3 , 0 , 0
       0     .06       0   294.1    .045       0   325.1     .08       0
Bank Sta=294.1,325.1
XS Rating Curve= 0 ,0
Exp/Cntr=0.3,0.1

Type RM Length L Ch R = 1 ,595.2   ,470.7,458.6,440.9
XS GIS Cut Line= 2
     1560055.139      274215.227     1560465.821      274552.177
#Sta/Elev= 30
       0   786.6    39.4  775.96    49.2  774.11      59  772.75    78.7  770.89
    88.5  769.47     118  763.54   127.9  762.36   137.7  761.63   147.6  761.38
   196.8  761.44   226.3  761.91   265.6  763.09   285.3  763.19     305  762.42
   314.8  761.59   355.4756.6032   363.9  756.13   373.8  756.18   381.4756.6967
   413.2  759.65     423  760.81   442.7  764.15   452.5   766.7   462.4  770.54
   472.2   773.8     482  776.16   491.9  779.68   521.4  795.82   531.2  800.21
#Mann= 3 , 0 , 0
       0     .06       0   355.4    .045       0   381.4     .06       0
Bank Sta=355.4,381.4
XS Rating Curve= 0 ,0
Exp/Cntr=0.3,0.1

Type RM Length L Ch R = 1 ,136.6   ,138.4,136.6,134.7
XS GIS Cut Line= 2
     1559899.535      274574.922     1560451.105      274581.072
#Sta/Elev= 30
       0  783.57     9.7   782.9      29  780.64    77.4  773.51    87.1  772.43
   116.1  770.06   125.8   768.3   135.5  765.13   145.2  760.87   154.9757.3273
   164.5   756.1   174.9757.2638   193.6  761.71   203.2  763.35   212.9  764.08
   241.9  764.18     271  765.01   290.3  765.12   319.4  764.72   367.7  763.22
   406.4  763.22   435.5  764.48   474.2  767.35   483.9  768.42   493.5   771.4
   503.2  776.72   522.6  788.48   532.2  794.06   541.9  798.28   551.6  800.79
#Mann= 3 , 0 , 0
       0     .06       0   154.9    .045       0   174.9     .06       0
#XS Ineff= 2 , 0
                          269.82          789.89
Permanent Ineff=
       F       F
Bank Sta=154.9,174.9
XS Rating Curve= 0 ,0
Exp/Cntr=0.3,0.1

Chan Stop Cuts=-1
Use User Specified Reach Order=0
Composite Channel Slope=5